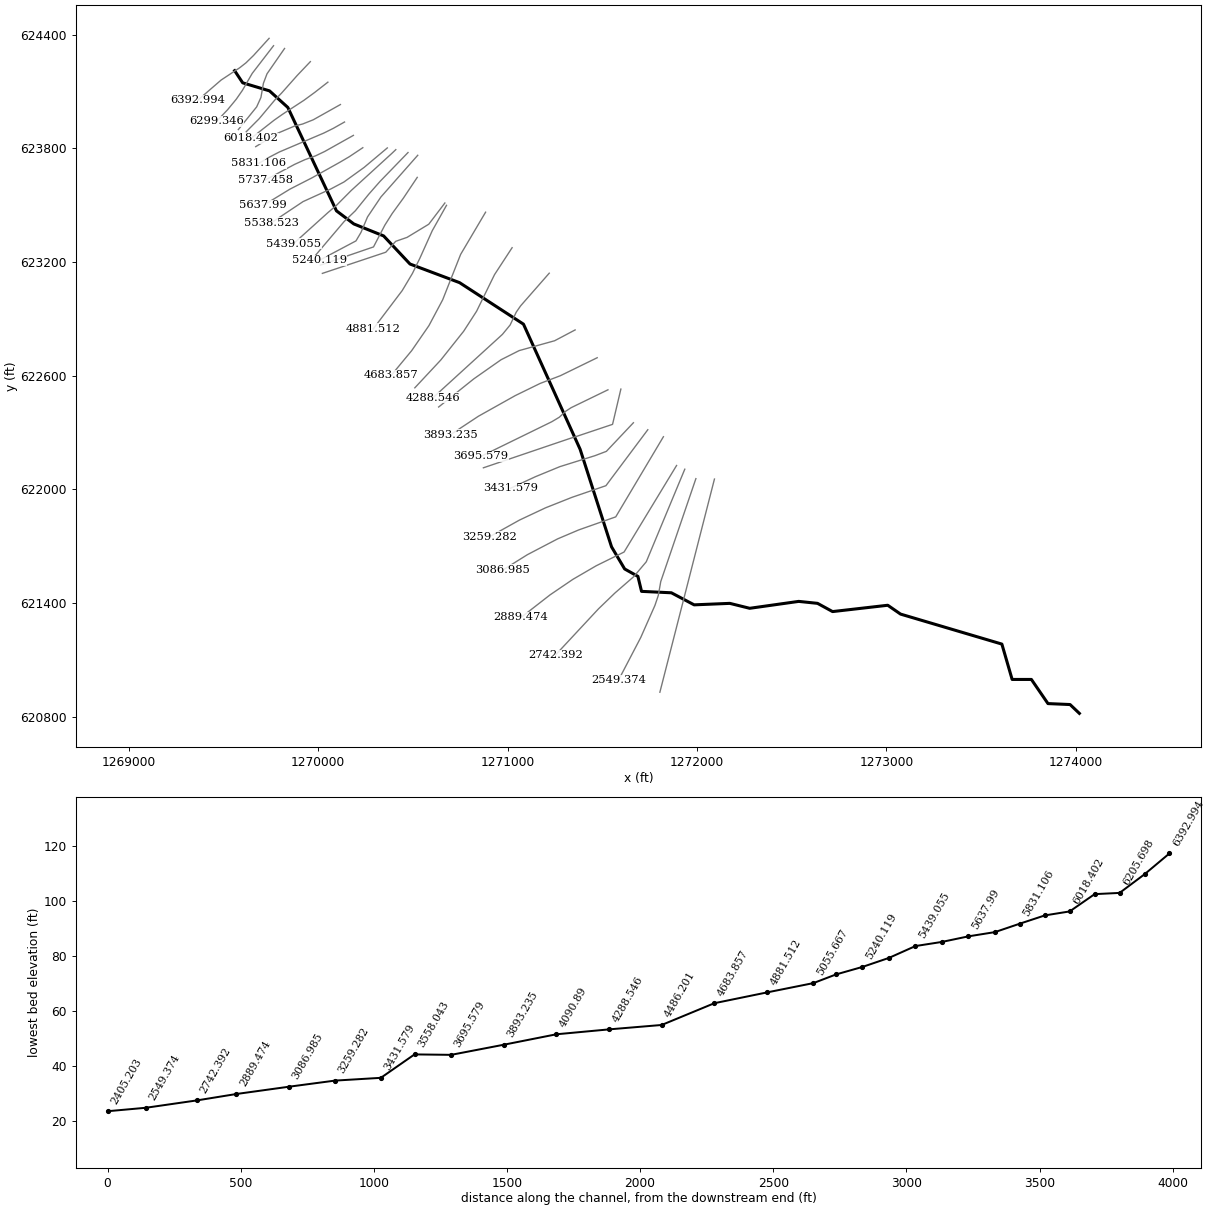
--- 544_ras.prj (project) ---

Proj Title=544
Current Plan=p01
Default Exp/Contr=0.3,0.1
English Units
Geom File=g01
Flow File=f01
Plan File=p01
Y Axis Title=Elevation
X Axis Title(PF)=Main Channel Distance
X Axis Title(XS)=Station
BEGIN DESCRIPTION:
RFD model 544 exported to HEC-RAS
END DESCRIPTION:

--- 544_ras.p01 (plan) ---

Plan Title=Plan 01
Program Version=4.10
Short Identifier=Plan 01
Geom File=g01
Flow File=f01
Subcritical Flow
Calc Critical at every XS
Secant Critical Depth

--- 544_ras.f01 (steady flow) ---

Flow Title=Flow 01
Program Version=5.01
Number of Profiles= 5
Profile Names=10yr,25yr,50yr,100yr,500yr
River Rch & RM=544,37,6392.994
  398.96  478.61  571.32  612.87  723.95
River Rch & RM=544,37,6299.346
  405.54  487.68  582.46  626.33  742.15
River Rch & RM=544,37,6205.698
  411.96  496.54  593.35  639.53  760.06
River Rch & RM=544,37, 6112.05
  415.12   500.9  598.71  646.04  768.91
River Rch & RM=544,37,6018.402
  419.78  507.36  606.66   655.7  782.05
River Rch & RM=544,37,5831.106
  428.14  518.94  620.91  673.07  805.77
River Rch & RM=544,37,5737.458
  464.61  569.92  683.76  750.21  912.17
River Rch & RM=544,37,5538.523
  501.29  621.78  747.87  829.82 1023.61
River Rch & RM=544,37,5439.055
  521.78     651  784.06  875.15 1087.76
River Rch & RM=544,37,5339.587
  526.17  657.29  791.84  884.93 1101.68
River Rch & RM=544,37,5240.119
  576.41   729.7  881.75  998.79 1265.12
River Rch & RM=544,37,5140.652
  577.36  731.08  883.46 1000.97 1268.28
River Rch & RM=544,37,4881.512
  622.81  797.42  966.05 1106.89 1422.79
River Rch & RM=544,37,4683.857
  651.67  839.91 1019.06 1175.48    1524
River Rch & RM=544,37,4486.201
  661.38  854.27 1036.99 1198.78 1558.57
River Rch & RM=544,37,4288.546
  665.21  859.93 1044.06 1207.99 1572.26
River Rch & RM=544,37, 4090.89
  669.75  866.67 1052.48 1218.95 1588.58
River Rch & RM=544,37,3893.235
  671.25   868.9 1055.27 1222.58 1593.99
River Rch & RM=544,37,3695.579
  697.49  907.93 1104.08 1286.41 1689.45
River Rch & RM=544,37,3558.043
  699.26  910.57 1107.37 1290.73 1695.94
River Rch & RM=544,37,3431.579
  700.31  912.15 1109.35 1293.32 1699.83
River Rch & RM=544,37,3259.282
  701.37  913.72 1111.32 1295.91 1703.72
River Rch & RM=544,37,3086.985
  737.48  967.84 1179.11 1385.21 1838.55
River Rch & RM=544,37,2889.474
  739.75  971.26 1183.39 1390.87 1847.14
River Rch & RM=544,37,2742.392
  749.36  985.73 1201.53 1414.89 1883.65
River Rch & RM=544,37,2549.374
  764.04 1007.89 1229.35  1451.8 1939.92
River Rch & RM=544,37,2405.203
  773.19 1021.74 1246.73 1474.92 1975.27
River Rch & RM=544,37,2189.568
   775.6 1025.39 1251.31 1481.03 1984.62
River Rch & RM=544,37,2046.227
  781.28 1034.01 1262.13 1495.45 2006.72
River Rch & RM=544,37,1862.178
  784.84 1039.41 1268.91  1504.5  2020.6
River Rch & RM=544,37, 1494.08
  793.63 1052.76 1285.68 1526.89 2055.01
River Rch & RM=544,37,1125.981
  805.11 1070.24 1307.66 1556.29  2100.3
River Rch & RM=544,37,757.8834
  808.79 1075.85 1314.71 1565.74 2114.88
River Rch & RM=544,37,205.7363
  818.02 1089.93 1332.42  1589.5 2151.59
Boundary for River Rch & Prof#=544,37,1
Up Type= 0
Dn Type= 2
Boundary for River Rch & Prof#=544,37,2
Up Type= 0
Dn Type= 2
Boundary for River Rch & Prof#=544,37,2
Up Type= 0
Dn Type= 2
Boundary for River Rch & Prof#=544,37,2
Up Type= 0
Dn Type= 2
Boundary for River Rch & Prof#=544,37,2
Up Type= 0
Dn Type= 2

--- 544_ras.g01 (geometry) ---

Geom Title=544
Program Version=4.10

River Reach=544,37
Reach XY= 30
1269558.64702504624210.7233054261269601.14701061624146.556656572
1269742.81363423624104.056665032 1269839.4802698624016.556688154
1270096.14684476623470.7235093611270187.81348234623401.556860578
1270345.31343396623338.2235414391270484.48005522 623189.89024803
 1270746.1466418623091.5569362551271083.64653578622872.390324784
 1271382.8130948622211.5571788931271548.64636408621696.557326944
 1271617.8130069621579.8906928911271687.81298512621540.724035793
1271706.97964381621461.5573920861271864.47959712621454.057389679
1271984.67444399 621390.405961351272173.04249954 621398.21846135
1272278.07722175621372.176794678 1272536.7577773621408.635128006
1272636.15690553621398.2978312981272715.57722178621354.815683559
1273006.97925799621388.2240424411273074.47923671621341.557387647
1273609.47907418621183.2240856541273663.64571936620996.557472779
1273765.31235603620996.5574698151273852.81232648620869.057505111
 1273969.4789586620864.0575031941274018.64560938620817.390848957

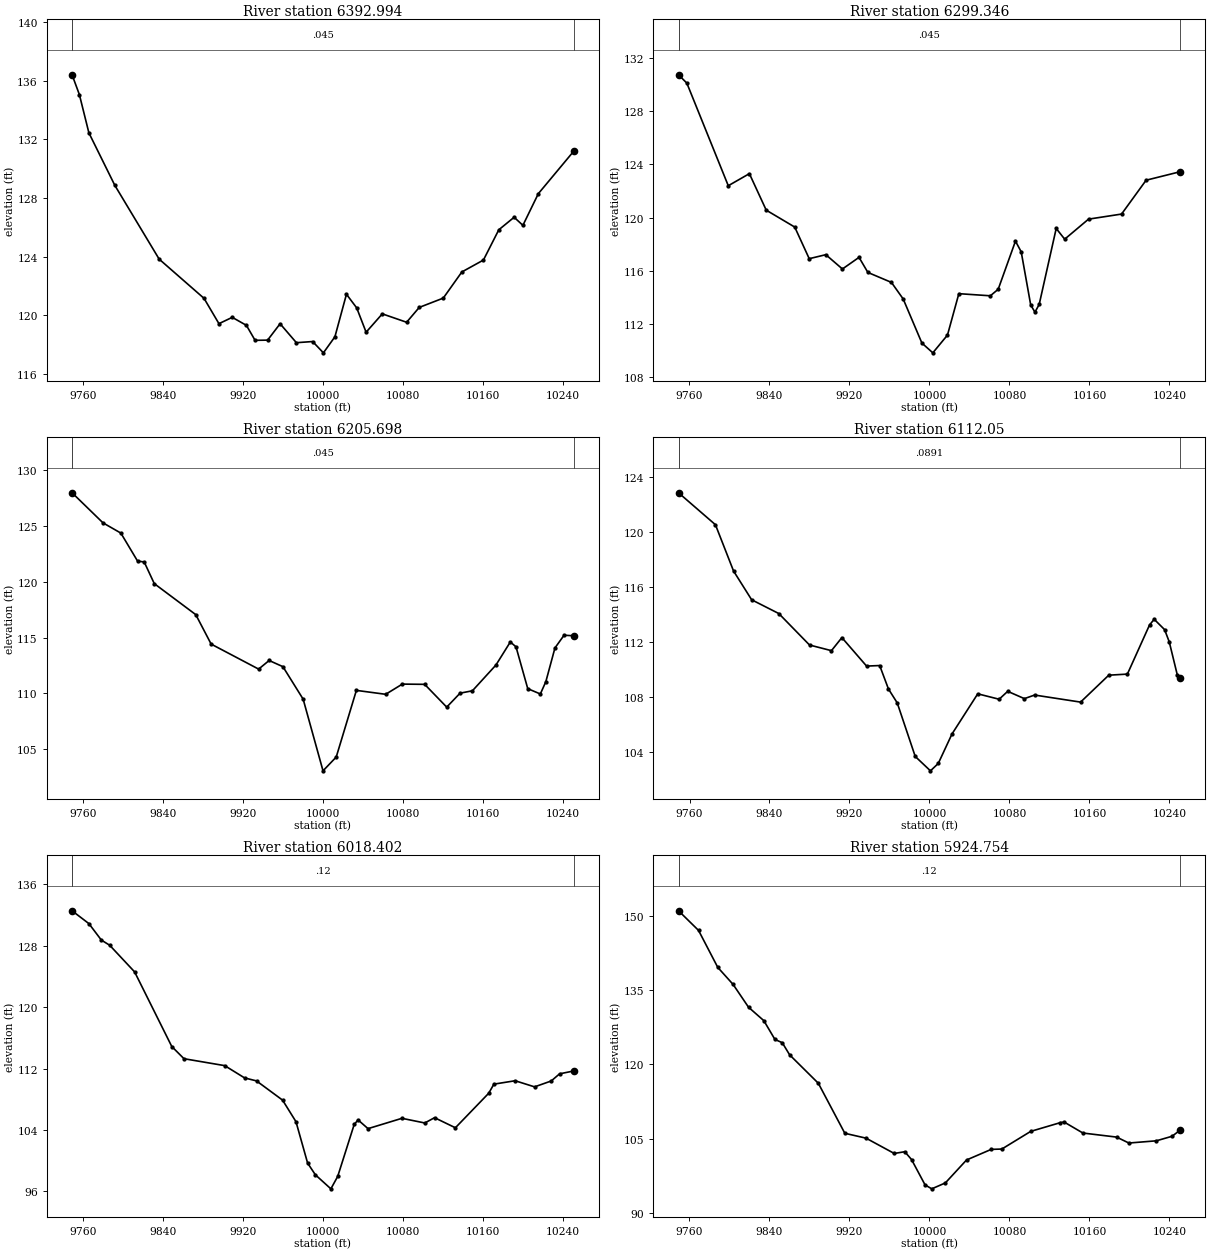
Type RM Length L Ch R = 1 ,6392.994,93.648000,93.648000,93.648000
XS GIS Cut Line= 6
1269740.66157211624381.4251851181269658.04035171624290.567546158
1269618.35652335 624251.943118011269585.84584434624226.435830733
1269487.38088525624161.2523011491269363.14146214624053.869226184
#Sta/Elev= 30
9749.055136.41659756.355 135.066 9765.87132.45399791.831128.86679836.176 123.831
9881.047121.15499895.966119.4264 9909.27119.85769923.436119.31229932.115118.2895
9944.625118.30229957.136119.42089973.432118.12799989.694118.206310000.45117.4351
10011.97 118.532 10023.5121.433910033.75 120.50510043.17118.842410059.37 120.096
10083.69119.522710096.31120.535810120.34121.171210138.93122.955810160.51123.7688
10175.88125.833510191.22126.690410199.99126.137510215.42128.299810250.97131.2109
#Mann= 3 , 0 , 0
9749.055   0.045       09749.055   0.045       010250.97   0.045       0
#XS Ineff= 2 , 0
       09981.238        10030.22       0
Bank Sta=9749.055,10250.97
Exp/Cntr=0.3,0.1

Type RM Length L Ch R = 1 ,6299.346,93.648000,93.648000,93.648000
XS GIS Cut Line= 6
1269764.11128863624342.4859617561269651.41185267624196.198571811
1269599.65270981624106.7361819881269567.10697728624059.813499821
1269521.26896651624004.2119084851269462.95023061623943.080298687
#Sta/Elev= 30
9749.041 130.7189757.352130.09189798.788122.38959819.907123.29539836.765120.5545
9865.279119.28549879.756 116.9139896.362117.21219912.969116.13929929.575117.0115
9938.423115.87999961.972115.13279973.746113.88779992.476 110.57610003.39109.8444
10018.03111.176110029.41114.285910060.93114.126710068.77114.616710086.04118.2306
10091.79117.426510101.28113.442410105.53 112.89510109.78113.480910126.79119.1801
10135.29118.376210159.11119.880410192.17120.262110216.72122.803310250.94123.4441
#Mann= 3 , 0 , 0
9749.041   0.045       09749.041   0.045       010250.94   0.045       0
#XS Ineff= 2 , 0
       0 9952.59        10041.93       0
Bank Sta=9749.041,10250.94
Exp/Cntr=0.3,0.1

Type RM Length L Ch R = 1 ,6205.698,93.648100,93.648100,93.648100
XS GIS Cut Line= 6
1269822.26965542624327.931376221 1269729.5796543 624194.13585785
1269710.65385609624144.3248731291269697.55809365624069.614080758
1269674.99364337624019.5284045351269578.19520599623899.765525906
#Sta/Elev= 30
9749.056127.98069779.969125.28699797.843 124.3699814.561121.86189821.202121.7815
9831.285119.84039872.798117.06099888.154114.42459935.658112.18349946.147112.9551
 9959.93112.40119980.176109.489510000.04103.068810013.25104.305210033.41110.2773
10062.71109.925710079.36110.840110101.71 110.81810123.76108.776510137.13110.0283
10149.46110.240210173.01112.549810187.37114.614710193.06114.177710204.81110.4309
 10217.4109.9545 10222.9111.0589   10232114.0774 10241.1115.217310250.92115.1698
#Mann= 3 , 0 , 0
9749.056   0.045       09749.056   0.045       010250.92   0.045       0
#XS Ineff= 2 , 0
       09945.152        10043.43       0
Bank Sta=9749.056,10250.92
Exp/Cntr=0.3,0.1

Type RM Length L Ch R = 1 , 6112.05,93.648000,93.648000,93.648000
XS GIS Cut Line= 6
1269958.46740725624258.4209183651269889.47149292624185.872337366
 1269805.0839268 624090.824142441269771.71498848624056.836096589
1269688.07132979623956.9684246671269619.83745804623888.299723952
#Sta/Elev= 30
9749.014122.87759785.934120.54999804.044117.18019822.155 115.0859849.315114.0826
9880.026111.79139901.962111.37899912.411 112.3319937.119110.25629950.223 110.296
9958.998108.58649967.772107.57559985.782103.6741   10001102.627310008.83103.1664
10022.55105.311510048.31108.236210069.71107.841710078.27108.417610094.96107.8862
10105.18108.147110151.17107.632910179.36109.593410197.98109.672210220.14113.2498
10224.77113.666510235.21112.910410239.87112.0181 10247.9109.617610250.94109.3608
#Mann= 3 , 0 , 0
9749.014  0.0891       09749.014  0.0891       010250.94  0.0891       0
#XS Ineff= 2 , 0
       0 9913.62        10063.45       0
Bank Sta=9749.014,10250.94
Exp/Cntr=0.3,0.1

Type RM Length L Ch R = 1 ,6018.402,93.648000,93.648000,93.648000
XS GIS Cut Line= 6
1270051.02091898624150.0761506611269980.52650664624095.176649883
1269924.90341254624054.5173628031269812.53147989623981.075376647
1269767.45627097 623949.509490781269645.92246965623854.237353693
#Sta/Elev= 30
 9749.01132.52869765.834130.85839778.309128.71589786.626128.04399811.576124.5757
 9848.76 114.8649860.951 113.2789901.725112.37559921.587110.7786 9933.51110.3897
9959.603107.88599972.996105.08179984.63399.694079992.39198.1711110007.9196.34306
10014.7497.9582410031.24104.721710035.12105.312210045.07 104.17610078.99105.5211
10101.86 104.91410111.62105.602510132.47104.290310165.82 108.78610170.99109.9677
10192.26110.409510211.67109.614110228.35110.380710236.68111.307410250.98111.6877
#Mann= 3 , 0 , 0
 9749.01    0.12       0 9749.01    0.12       010250.98    0.12       0
#XS Ineff= 2 , 0
       0 9918.25        10063.21       0
Bank Sta=9749.01,10250.98
Exp/Cntr=0.3,0.1

Type RM Length L Ch R = 1 ,5924.754,93.648000,93.648000,93.648000
XS GIS Cut Line= 6
1270117.13204553624031.8581232951269973.59390604623951.314275015
1269917.33569852623928.9944976021269876.40495996623918.822184857
1269787.79456169623881.3221585861269669.92494722623809.561457047
#Sta/Elev= 30
9749.124150.98119769.116147.02619788.352139.56369803.741136.1114 9819.13131.5219
9834.455128.80699845.504125.0279 9852.87124.36359860.236121.91579888.918116.1833
9915.414 106.0929936.592  105.119964.828102.02299975.372102.37359982.128100.7935
 9995.6495.6849410002.3594.8845810015.97 96.081910037.11100.703810061.81102.8457
10072.42 102.91210101.32106.477910130.92108.239910134.68108.365910153.48106.1445
10187.19 105.32310199.45 104.12710226.92104.573410242.62105.488310250.91 106.757
#Mann= 3 , 0 , 0
9749.124    0.12       09749.124    0.12       010250.91    0.12       0
#XS Ineff= 2 , 0
       09947.731        10069.09       0
Bank Sta=9749.124,10250.91
Exp/Cntr=0.3,0.1

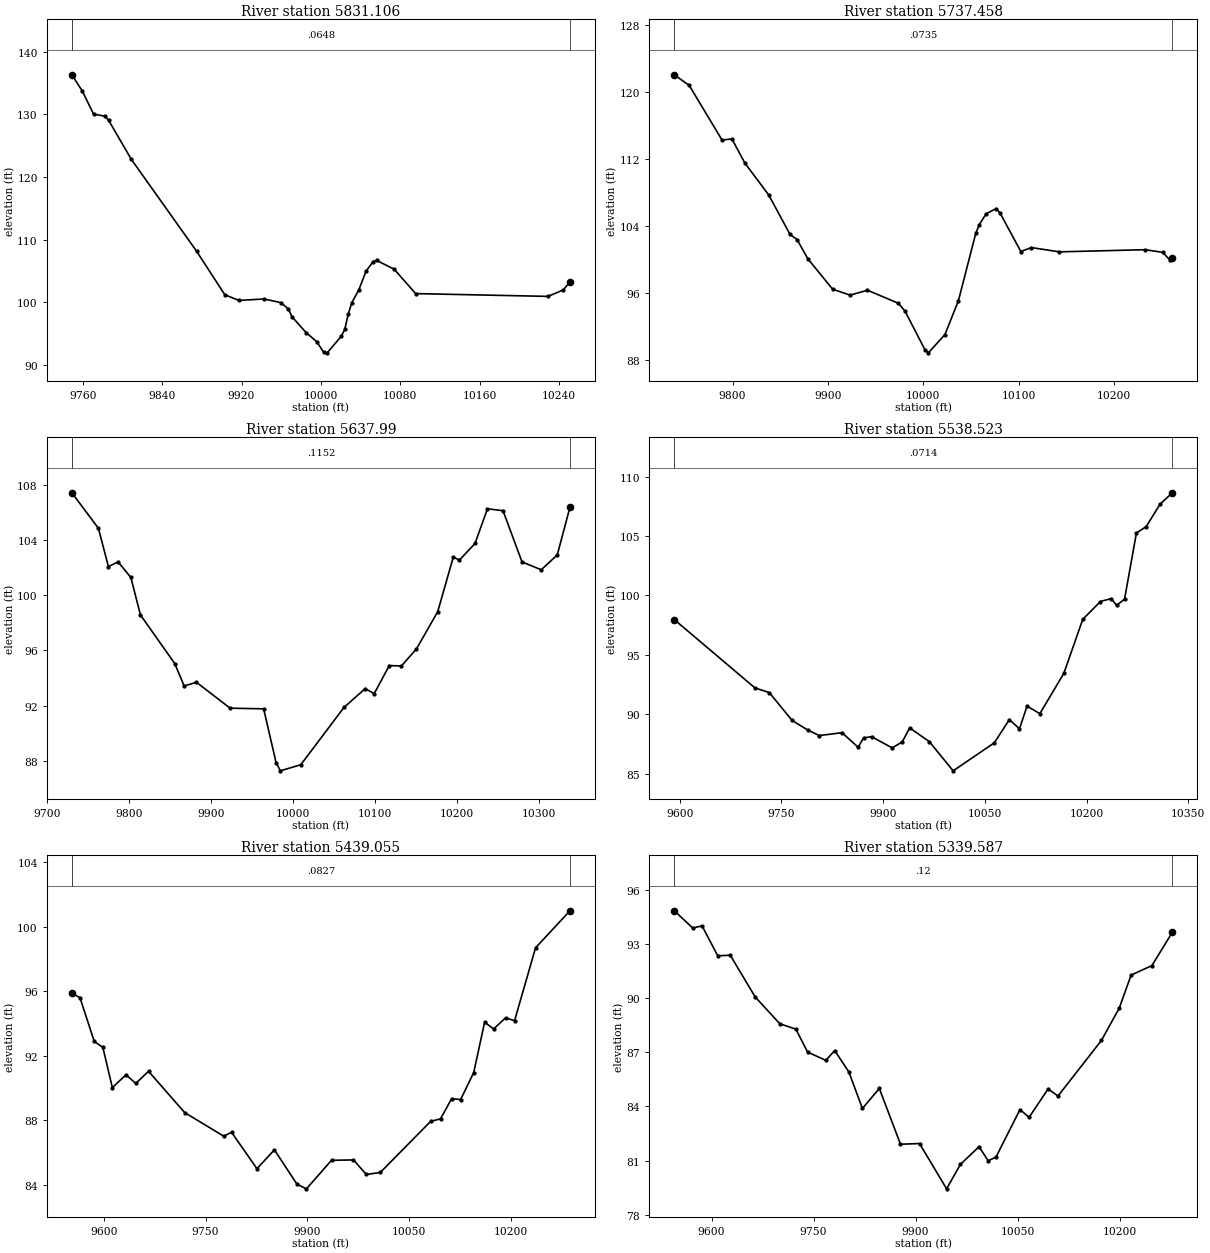
Type RM Length L Ch R = 1 ,5831.106,93.648000,93.648000,93.648000
XS GIS Cut Line= 6
1270138.80714953623939.6209489581270079.27135952623905.988288104
1270029.14422592623881.1465715951269794.66643643623781.425145546
1269742.27952375623754.2369865071269687.26731406623721.972045911
#Sta/Elev= 30
9749.034136.33539759.596 133.7139770.901130.04699782.205 129.7259785.973129.0857
 9808.96122.81039874.702108.13459903.163101.17059917.394100.26839942.584 100.501
9959.54999.920889967.20298.91486 9970.7697.671559984.99795.135079995.66493.69347
10002.7991.9854810006.3491.8894910020.5594.54393 10024.195.6639410027.6198.13978
 10031.299.92234 10038.3101.9846 10045.4 104.924 10052.5106.458710056.05106.6703
10073.82105.258810095.43101.357910228.82100.912110244.03101.925110250.98103.2225
#Mann= 3 , 0 , 0
9749.034  0.0648       09749.034  0.0648       010250.98  0.0648       0
#XS Ineff= 2 , 0
       09936.308           10062       0
Bank Sta=9749.034,10250.98
Exp/Cntr=0.3,0.1

Type RM Length L Ch R = 1 ,5737.458,99.467700,99.467700,99.467700
XS GIS Cut Line= 6
1270185.69697815623869.0465099841270034.65866285623784.349203739
1269986.54539548623761.2476434961269929.50744585623740.719707135
1269874.86289362623715.7355674671269720.57761845623633.589300881
#Sta/Elev= 30
9738.937122.01349754.603120.74539789.032114.2176 9799.37114.3576 9812.82111.4955
9838.029107.64919860.333102.94369867.767102.33079878.919100.0499 9904.9496.41463
9923.28895.703029941.48596.290719973.89394.727019980.922 93.778310001.8189.16282
10005.2988.81383 10022.790.9960710036.8795.0609710055.04103.098310058.65 104.107
10065.86105.414710076.32106.039310080.29 105.54210102.23100.913410113.26101.3832
10142.66100.872510232.42101.1274   10251100.812710258.5499.8804510261.08100.1812
#Mann= 3 , 0 , 0
9738.937  0.0735       09738.937  0.0735       010261.08  0.0735       0
#XS Ineff= 2 , 0
       09937.749        10072.24       0
Bank Sta=9738.937,10261.08
Exp/Cntr=0.3,0.1

Type RM Length L Ch R = 1 , 5637.99,99.467700,99.467700,99.467700
XS GIS Cut Line= 6
1270235.31557584623804.0145860911270163.77876827 623756.30137834
1270113.83493745623726.9447064251269968.27295324623645.537740961
1269850.42005447623585.0890521111269709.76969916623499.097618982
#Sta/Elev= 30
9730.236107.41279762.592104.8421 9774.86102.06459786.588102.41119802.225101.2817
9813.95398.564789855.87695.043649867.29393.421429882.34593.689519923.35491.81557
9964.38591.766719979.51487.878339984.76787.2768310009.7687.7214910062.4791.87129
10088.2893.2272110099.3492.8702710117.77 94.900410132.5294.8695910150.9696.10941
10176.8798.8001710195.86102.749610203.46102.544110222.45103.743310237.64106.2562
10256.63106.113810279.79102.404410303.26101.836510322.82102.909210338.34 106.368
#Mann= 3 , 0 , 0
9730.236  0.1152       09730.236  0.1152       010338.34  0.1152       0
#XS Ineff= 2 , 0
       09952.928        10124.43       0
Bank Sta=9730.236,10338.34
Exp/Cntr=0.3,0.1

Type RM Length L Ch R = 1 ,5538.523,99.467700,99.467700,99.467700
XS GIS Cut Line= 6
1270364.76095572623802.8553109321270242.29455024623699.952616498
1270135.77926707623622.9260846381270066.24040768 623586.05645071
1269919.95973471623519.4632141741269750.80083093623406.545002058
#Sta/Elev= 30
 9591.9397.971779710.85792.226689732.11691.833759765.67889.491769789.56788.65759
9805.86388.217929839.38788.458329863.13587.234739871.05288.015549882.92688.12583
9913.33987.180159928.19587.680179939.13588.865329968.10487.7077310003.3185.24954
10064.0987.6109310086.2289.5608810101.1288.78755 10112.390.6956610131.1890.06024
10166.5893.4522110194.42 97.985210220.4699.4904910236.3399.7375610244.4299.16777
10256.0999.68889 10273.6105.252510288.07105.793710308.43107.6753 10326.6 108.636
#Mann= 3 , 0 , 0
 9591.93  0.0714       0 9591.93  0.0714       0 10326.6  0.0714       0
#XS Ineff= 2 , 0
       0 9946.85        10146.63       0
Bank Sta=9591.93,10326.6
Exp/Cntr=0.3,0.1

Type RM Length L Ch R = 1 ,5439.055,99.467800,99.467800,99.467800
XS GIS Cut Line= 6
1270409.53250268623793.7182605271270387.54730427623772.891548648
1270174.40944204623578.2489499751270096.89436093623500.230257317
1270052.51798111623462.4423926621269868.80770639 623296.71093522
#Sta/Elev= 30
9552.911 95.89749564.89895.597369585.94592.888659598.59292.525919612.60490.02385
9632.64890.822739647.244 90.2853 9665.9291.042559719.23788.478359776.99787.01022
9788.33687.25802 9825.8784.995689851.58486.166339884.95984.031449898.83383.74622
9935.83285.517429968.20685.539849987.15284.63681 10007.884.7627110081.93 87.9278
10096.6288.0908210113.0289.3384710126.2789.28693 10145.6  90.96310161.6294.08286
10174.99  93.66810192.5594.3561910205.81 94.178210236.7498.6985410287.52100.9975
#Mann= 3 , 0 , 0
9552.911  0.0827       09552.911  0.0827       010287.52  0.0827       0
#XS Ineff= 2 , 0
       0 9928.78                       0
Bank Sta=9552.911,10287.52
Exp/Cntr=0.3,0.1

Type RM Length L Ch R = 1 ,5339.587,99.467700,99.467700,99.467700
XS GIS Cut Line= 6
1270474.08548328623778.4972714781270326.30344307623625.980097786
1270265.79935026623557.2994622441270196.33246204623471.433525518
1270136.64533231623413.9907241311269984.57925934623234.691993088
#Sta/Elev= 30
 9545.1794.834279572.23593.882629586.05993.997549609.09992.341629627.53292.37291
9664.09390.065289700.36188.580189724.04188.276659741.16387.01213 9767.9886.55109
9781.09787.094099801.97885.90392 9821.8383.886979846.68284.99687 9877.8281.90816
9905.84681.943899945.63279.436799965.891 80.78749993.26481.7700510006.78 80.9926
10018.2181.1942110053.5283.8251910066.9483.3974510094.8784.96897 10109.484.57566
10173.2287.6528110199.4489.4377810216.9291.2727710247.5191.7995610277.5793.64414
#Mann= 3 , 0 , 0
 9545.17    0.12       0 9545.17    0.12       010277.57    0.12       0
#XS Ineff= 2 , 0
       09910.086                       0
Bank Sta=9545.17,10277.57
Exp/Cntr=0.3,0.1

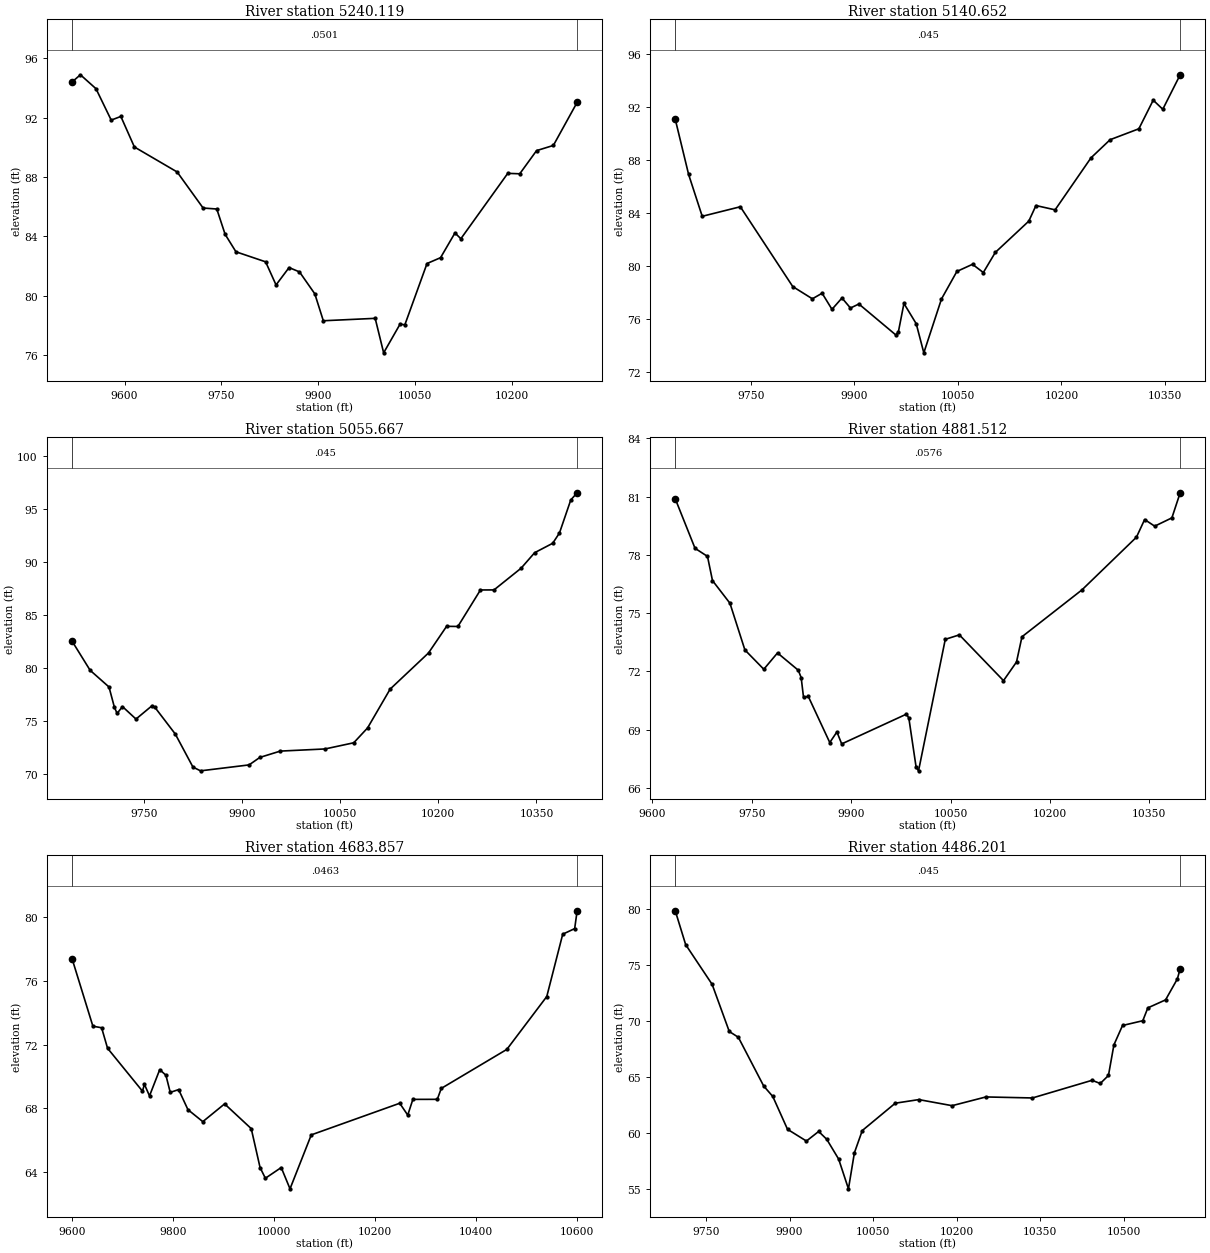
Type RM Length L Ch R = 1 ,5240.119,99.467700,99.467700,99.467700
XS GIS Cut Line= 6
1270525.37363014623764.0159123841270330.94365028 623543.75877735
1270260.33685997623438.6634231511270225.77934831623356.881507769
1270199.23607594623311.9228884281270005.22565925623209.058305085
#Sta/Elev= 30
9519.08694.413559531.74394.888679555.81893.952899579.41891.835049594.33792.08235
9615.27990.024939681.43888.341359721.61585.913279742.79785.846439755.66584.14334
9772.44182.964789818.36182.289199834.486 80.73249854.64381.902269870.76881.61034
9894.47380.133529907.64878.319659987.90578.48275   1000176.1587310026.3978.09109
10033.8278.0483110068.1182.1750110089.0882.5692710111.36 84.235310120.4883.84472
10193.0688.2485510211.6288.2195110237.6289.7795210263.6190.1288710300.4293.03186
#Mann= 3 , 0 , 0
9519.086  0.0501       09519.086  0.0501       010300.42  0.0501       0
#XS Ineff= 2 , 0
       09877.048                       0
Bank Sta=9519.086,10300.42
Exp/Cntr=0.3,0.1

Type RM Length L Ch R = 1 ,5140.652,84.984500,84.984500,84.984500
XS GIS Cut Line= 6
1270522.78208286623647.3829578911270448.71745974623536.443814263
1270390.92660886623457.1505773071270351.80059034623395.250805855
1270291.87930512623280.1954578911270010.62930512623183.841291204
#Sta/Elev= 30
9640.35291.06713 9659.7286.896499679.44483.735079734.671 84.45669810.66778.42533
9839.08677.501779853.19677.923039867.50476.705319881.98777.563579894.26876.80397
9906.50877.108489960.06974.768489963.75975.008719971.78277.148269989.589 75.6192
10000.6173.4187210026.2277.4902210048.5379.5695710071.1980.1081710086.8479.48518
10104.1881.0044410152.7383.3684110163.13 84.548610190.8884.22312 10242.988.15302
10270.6489.5236810312.26 90.347610333.07 92.508710346.9491.8234110372.14 94.4284
#Mann= 3 , 0 , 0
9640.352   0.045       09640.352   0.045       010372.14   0.045       0
#XS Ineff= 2 , 0
       09876.755                       0
Bank Sta=9640.352,10372.14
Exp/Cntr=0.3,0.1

Type RM Length L Ch R = 1 ,5055.667,174.155100,174.155100,174.155100
XS GIS Cut Line= 6
 1270668.6154162623511.9662912191270583.54597178623399.987124532
1270468.96263844  623330.54268011270409.06680509623309.709346771
1270356.72093204623252.2094982271270021.91402733623140.438513443
#Sta/Elev= 30
9640.924 82.4826 9668.2679.757849697.10178.182759705.34176.266869709.46275.68854
9717.70276.331639738.30375.156699763.024 76.42429767.23276.259399798.36373.74116
9825.357 70.62139836.92570.270389911.08170.830799927.48871.53713 9958.75 72.1334
10027.0872.33566 10070.972.9178310092.0274.31905 10126.577.9828410185.1281.39516
10212.7183.9070410229.95  83.89310264.4387.3384510285.1287.3421910326.4989.38995
10347.1890.8535210374.7791.7439610385.11 92.715510402.3595.82783 10412.196.50869
#Mann= 3 , 0 , 0
9640.924   0.045       09640.924   0.045       0 10412.1   0.045       0
#XS Ineff= 2 , 0
       09841.509                       0
Bank Sta=9640.924,10412.1
Exp/Cntr=0.3,0.1

Type RM Length L Ch R = 1 ,4881.512,197.655500,197.655500,197.655500
XS GIS Cut Line= 6
1270677.29597178623499.8135134281270601.77513841623365.264902309
1270536.85021311623220.9734411241270497.19585007623139.859885871
1270443.68809092623050.0751988591270290.14319396622847.035735667
#Sta/Elev= 30
9634.61380.887619664.44978.339799683.26177.922969690.78576.678479717.12275.51322
9739.69673.108789768.23472.114489788.907 72.95459820.21772.065049824.59571.68797
9828.19370.664319835.38870.714069867.767  68.343 9878.5668.888629885.75668.27193
9983.43169.804599987.08369.603989998.03967.0772310001.6966.8861510042.0773.65518
10063.3173.8842210129.9171.5279910149.5572.4886410157.7873.7859610248.2776.19866
10330.5478.9127510342.8879.8206210358.0579.4787510384.0179.90618 10396.581.19747
#Mann= 3 , 0 , 0
9634.613  0.0576       09634.613  0.0576       0 10396.5  0.0576       0
#XS Ineff= 2 , 0
       0 9840.57        10035.44       0
Bank Sta=9634.613,10396.5
Exp/Cntr=0.3,0.1

Type RM Length L Ch R = 1 ,4683.857,197.655500,197.655500,197.655500
XS GIS Cut Line= 6
 1270883.6211457623463.5516545771270751.80462301623240.571436197
1270657.15911931623001.2169626951270584.57433638622864.781811163
1270493.28833687622732.4184185711270385.59647563622602.386116609
#Sta/Elev= 30
9599.87277.349779640.84273.15253 9658.15 73.05469669.90171.771239739.16669.08115
9742.96669.514459753.093 68.78519773.359 70.43049785.62770.080079794.18869.00574
9810.84869.180529829.28967.923559858.79367.171969901.97868.284579954.79166.73463
9972.30564.295539982.81463.6251110014.2564.2972910031.66 62.962410073.8366.34306
10249.1668.3240910265.09 67.582310275.2668.56725 10323.768.5703510331.5569.25364
10461.5871.6997410540.7475.0121510572.3478.9158410596.0479.2657710600.9480.38353
#Mann= 3 , 0 , 0
9599.872  0.0463       09599.872  0.0463       010600.94  0.0463       0
#XS Ineff= 2 , 0
       0 9942.16        10088.12       0
Bank Sta=9599.872,10600.94
Exp/Cntr=0.3,0.1

Type RM Length L Ch R = 1 ,4486.201,197.655500,197.655500,197.655500
XS GIS Cut Line= 6
1271023.63744339623276.0374019741270930.78434166623133.859539226
1270836.19310567622940.7058685271270767.92365956622835.026382849
1270646.99664664622682.9983449581270509.96631745622536.229913339
#Sta/Elev= 30
9694.73679.846639713.43276.825939760.93273.28398 9791.6969.082559807.98468.56447
9853.44464.221259869.80763.285819896.21860.359939930.17659.311139952.12260.16762
9966.654 59.46739987.96557.7069710005.5955.0507410016.2558.2625410030.4260.24929
10089.62 62.687910131.8963.0090410191.5762.4665510252.27 63.245210335.8363.15522
10442.79 64.7295 10457.564.4448510472.2165.1590210482.0267.88856 10497.569.61832
10533.8470.0415810542.9271.1885810574.7371.9008710595.8873.7686710600.9474.67711
#Mann= 3 , 0 , 0
9694.736   0.045       09694.736   0.045       010600.94   0.045       0
#XS Ineff= 2 , 0
       09953.451        10117.91       0
Bank Sta=9694.736,10600.94
Exp/Cntr=0.3,0.1

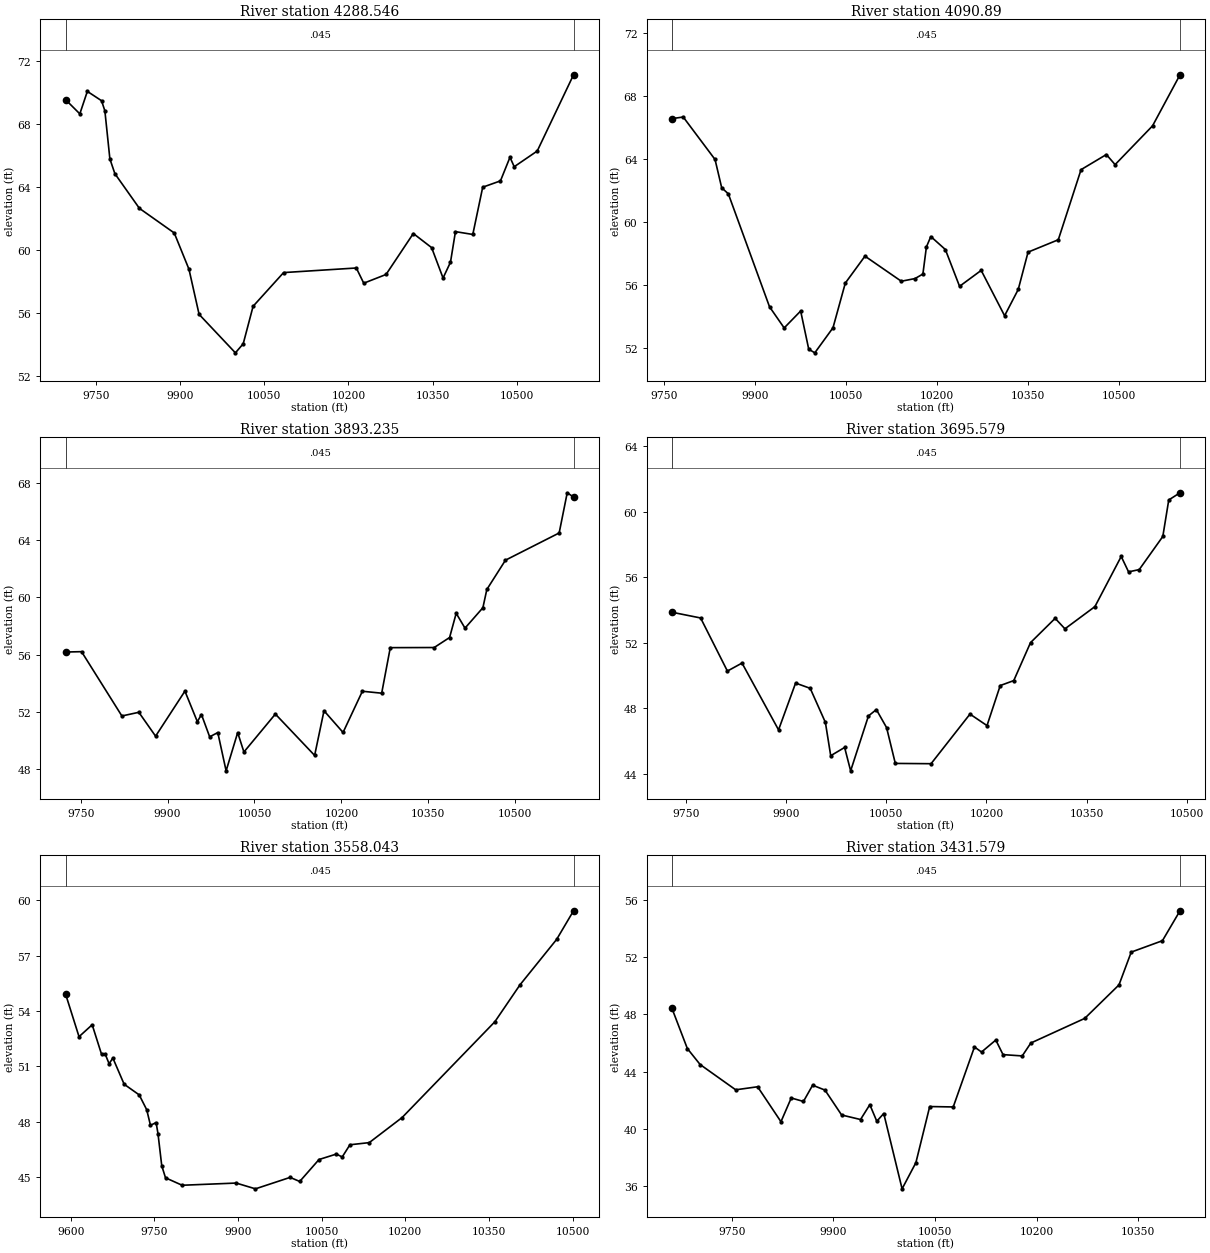
Type RM Length L Ch R = 1 ,4288.546,197.655500,197.655500,197.655500
XS GIS Cut Line= 6
1271219.66663879623141.5052833411271068.58946607622969.045526236
1271045.41460094622935.7444288131271013.18105173622867.921171397
1270972.45013842622818.3468162421270606.48117372 622484.45833908
#Sta/Elev= 30
9695.99769.537959721.50268.630329734.88370.059569760.15769.466699766.10868.82514
9775.02965.77149 9783.9564.831249827.61862.629659889.69961.064439915.91558.76172
9933.94955.895189998.61953.4507810012.5554.0276610030.15 56.409610084.4658.54858
10213.9858.8404510227.22 57.874110266.9558.4290610315.5161.0305210348.1460.13332
10368.4958.2019710381.7359.2090510390.5661.1499610421.4660.9705910439.1263.97257
10470.7364.3732710487.6865.8734710495.24 65.273310536.2466.2701810600.9271.11354
#Mann= 3 , 0 , 0
9695.997   0.045       09695.997   0.045       010600.92   0.045       0
#XS Ineff= 2 , 0
       0                10139.83       0
Bank Sta=9695.997,10600.92
Exp/Cntr=0.3,0.1

Type RM Length L Ch R = 1 , 4090.89,197.655500,197.655500,197.655500
XS GIS Cut Line= 6
1271356.34155259622841.9132677471271248.04517159622784.729045555
1271061.08314952 622732.837737531270965.48898166622684.596568331
1270821.19920143622583.4190720921270635.84483042622434.978074923
#Sta/Elev= 30
9762.84266.53418 9781.4266.635969833.89663.939629844.849 62.14719855.80261.76022
9923.764 54.59019947.92453.248199975.11554.321799988.44451.90014 9998.4451.66742
10028.4653.2587610048.7856.0957610081.2157.8046510141.15 56.211910163.7356.38124
10176.7656.6699710182.54 58.387110189.8259.0499710213.8358.2242110237.2455.88976
10272.9256.9007410311.5454.0212810334.0555.6914210350.2358.0592210400.1258.84528
10437.6663.2952210479.3864.2542410493.8263.61439 10555.666.07567 10600.969.31707
#Mann= 3 , 0 , 0
9762.842   0.045       09762.842   0.045       0 10600.9   0.045       0
#XS Ineff= 2 , 0
       0                10119.25       0
Bank Sta=9762.842,10600.9
Exp/Cntr=0.3,0.1

Type RM Length L Ch R = 1 ,3893.235,197.655500,197.655500,197.655500
XS GIS Cut Line= 6
1271472.91983691622695.145078823 1271278.6344763622600.284747794
1271171.36119008622559.2384846511271040.37210262622495.210144535
1270845.97604623622386.3401775661270698.00336403622288.569783181
#Sta/Elev= 30
9723.66256.183369751.37656.208589821.02651.708469850.28751.966389879.22550.29463
9929.86653.447269951.33751.309269958.42851.811119972.60950.248819986.624  50.547
   1000147.8692510020.9950.5456610031.7349.1862210086.0551.8420210153.85 48.9475
10170.0452.0742910202.9450.55453 10236.353.4383710269.6553.3022510284.4856.48954
 10360.356.49792 10386.957.19862 10398.358.89445 10413.557.8540810444.4159.28321
10451.2160.5600310483.3862.6102910576.1164.5146410590.0267.3271410600.9567.02946
#Mann= 3 , 0 , 0
9723.662   0.045       09723.662   0.045       010600.95   0.045       0
#XS Ineff= 2 , 0
       09924.013        10094.76       0
Bank Sta=9723.662,10600.95
Exp/Cntr=0.3,0.1

Type RM Length L Ch R = 1 ,3695.579,137.536700,137.536700,137.536700
XS GIS Cut Line= 6
1271529.72958174 622525.790147261271335.44324341622431.463236764
1271307.73947394622413.3295893221271272.57400104622380.831647113
1271232.90087876622357.0679453911270857.85152733622173.641638443
#Sta/Elev= 30
9729.14253.86742 9772.0253.517429812.13850.277269834.02150.765229888.72646.68847
9914.25649.544479936.13849.223489958.87447.144119966.83345.111379987.65845.61606
9996.66444.1887210023.3647.54057 10035.247.92707 10050.546.8266510063.56 44.6414
 10117.144.6240810175.3747.6514910200.8646.9499410220.6749.3935610240.9249.69562
10266.0252.01216 10302.953.4951410317.56 52.855410362.4554.2117710401.8257.27116
10412.8256.3314310428.7956.4695410464.1158.4898210473.0160.7195310489.8761.15781
#Mann= 3 , 0 , 0
9729.142   0.045       09729.142   0.045       010489.87   0.045       0
#XS Ineff= 2 , 0
       0 9930.98        10112.32       0
Bank Sta=9729.142,10489.87
Exp/Cntr=0.3,0.1

Type RM Length L Ch R = 1 ,3558.043,126.463300,126.463300,126.463300
XS GIS Cut Line= 5
1271597.86888844622529.5444162191271553.96528277622343.336261228
1271367.68506268622281.0161769691271331.78724909622269.885119319
1270871.95743009622113.962818995
#Sta/Elev= 30
9590.74154.926749614.98352.602459638.57953.249059655.43351.641019662.17451.63759
9668.91651.133969675.65851.445119695.88250.022799722.84949.446169736.33248.64062
9743.07347.795889753.18647.943279756.55747.342369763.29845.60078 9770.0444.94814
9799.85144.543659896.71944.663019931.31544.34947 9993.4844.9706410010.6544.74872
10045.2545.9397910076.43 46.236310086.8246.0770110100.6846.7400110135.3246.85624
10194.2248.21654 10360.553.4118110405.54 55.413210471.3657.8820910501.6159.43201
#Mann= 3 , 0 , 0
9590.741   0.045       09590.741   0.045       010501.61   0.045       0
#XS Ineff= 2 , 0
       0 9945.21        10062.88       0
Bank Sta=9590.741,10501.61
Exp/Cntr=0.3,0.1

Type RM Length L Ch R = 1 ,3431.579,172.296900,172.296900,172.296900
XS GIS Cut Line= 6
1271664.07982591622351.8534439951271521.34519628622200.809255376
1271461.00103489622177.9345797751271275.71524525622120.025522798
1271146.40103751622066.8258461361271015.66794178622006.171482623
#Sta/Elev= 30
9661.387 48.42159684.09945.621059702.97844.506719755.523 42.7424 9787.9242.95434
9822.39840.515369837.57442.17132 9855.6341.929739869.17243.063399887.45342.72155
9912.01440.984779939.94940.668959953.68941.703759963.99440.548379974.25841.08882
10001.36 35.831310021.7637.6590210042.1641.5739910076.9141.5461310108.2645.73142
10118.7145.3779410139.8146.2147910150.4745.1975710178.8545.1066910191.5546.00699
10271.1547.7251210321.7850.0630410339.8752.3513910385.97 53.147310411.9555.23581
#Mann= 3 , 0 , 0
9661.387   0.045       09661.387   0.045       010411.95   0.045       0
#XS Ineff= 2 , 0
       09950.762        10053.52       0
Bank Sta=9661.387,10411.95
Exp/Cntr=0.3,0.1

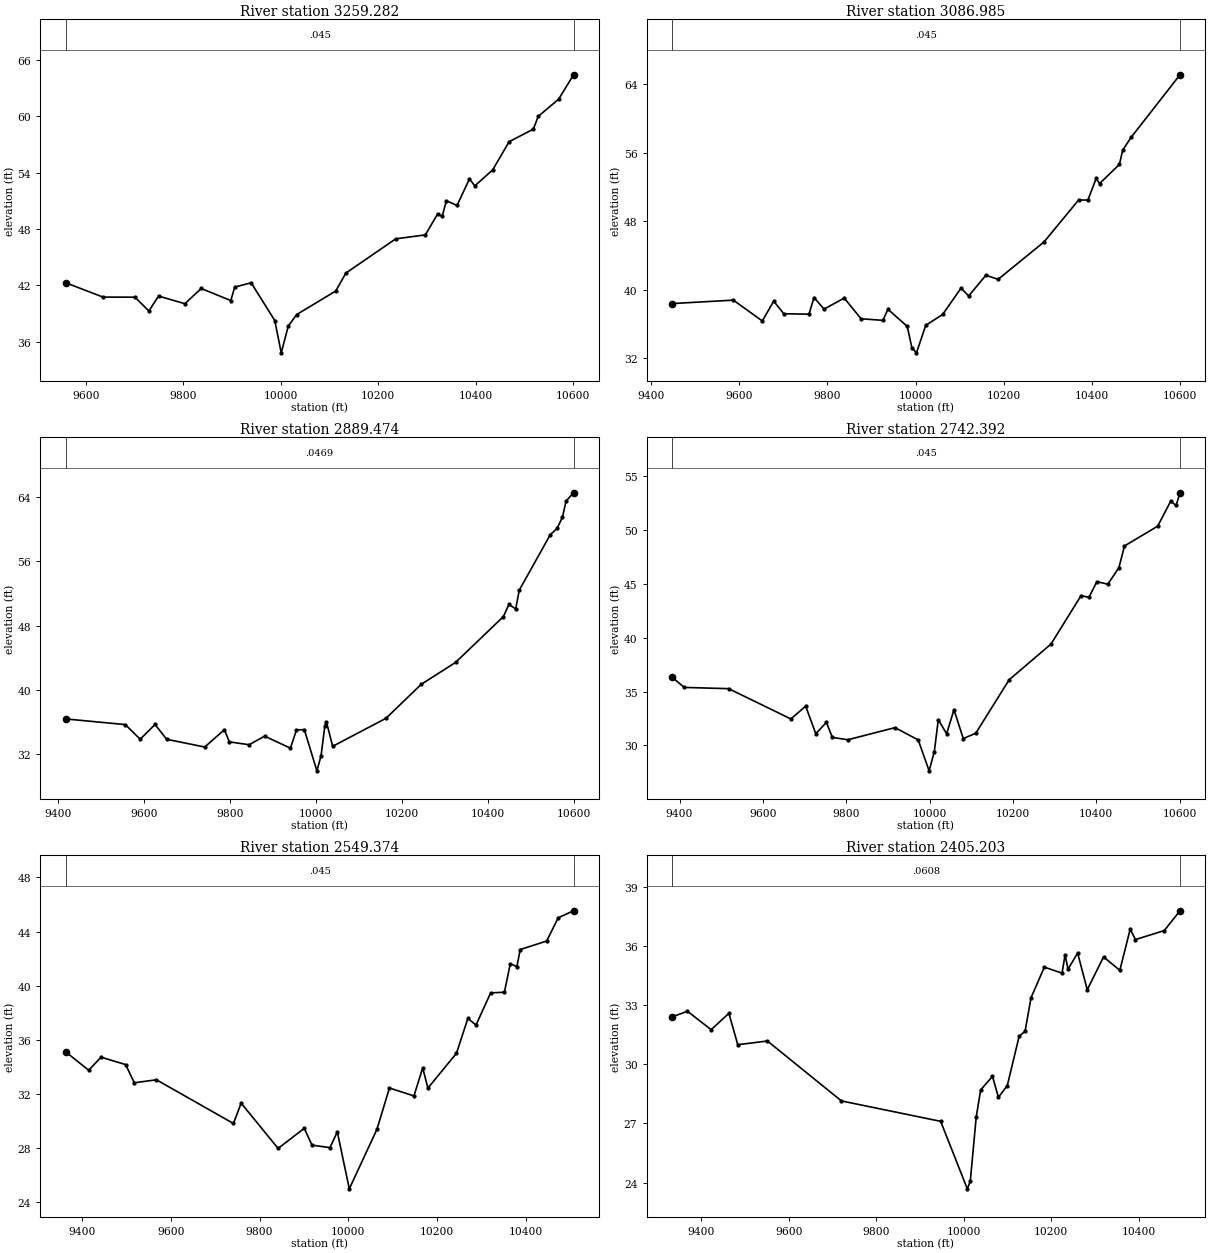
Type RM Length L Ch R = 1 ,3259.282,172.296800,172.296800,172.296800
XS GIS Cut Line= 6
1271740.03468704622314.9610828911271518.98848978622019.515348017
1271339.94094321621958.1031079591271199.87871429621902.544951946
1271062.81993046621838.1226358861270903.62874711621749.300888255
#Sta/Elev= 30
9558.22142.285429635.19940.751799700.758 40.7407 9729.4439.270119749.12440.86182
9803.19440.047519836.74941.665729897.43640.380899905.63141.81824 9939.2742.27189
 9987.7638.25426   1000134.8213910015.5137.6830910032.8638.8980510112.7141.39044
10133.7243.3063410236.0346.9474110296.7847.3680810321.9949.5913510331.5349.36926
10339.9950.9936610361.7750.5003410387.3653.3236410398.3352.5833110435.1654.28611
 10468.657.2743810518.38 58.615310528.6259.9785210570.3461.7985610600.9864.39766
#Mann= 3 , 0 , 0
9558.221   0.045       09558.221   0.045       010600.98   0.045       0
#XS Ineff= 2 , 0
       09939.965        10056.74       0
Bank Sta=9558.221,10600.98
Exp/Cntr=0.3,0.1

Type RM Length L Ch R = 1 ,3086.985,197.511900,197.511900,197.511900
XS GIS Cut Line= 6
 1271822.4999648622278.0687217561271570.76385373621854.891638428
1271375.77689156621786.1598998311271264.33495849621738.895222872
1271104.62130213621655.4335912761270974.12605917621573.993685603
#Sta/Elev= 30
9446.63438.36776 9586.1338.768759651.945 36.32979677.74938.654269700.65437.17811
9757.91537.126849769.36839.075319792.27237.718599838.08239.011969876.25636.59091
9925.88336.405799937.33537.697199981.35435.696179991.70833.1994310002.16 32.6068
10023.2135.8245910061.5637.0910410103.3940.1718210120.8239.2579410159.8841.68083
10187.67 41.200310291.9645.5745710370.3950.46759 10391.7 50.4829 10410.452.99369
10418.1952.4059610463.1654.6318110470.82 56.308710490.0557.8209610600.9765.12211
#Mann= 3 , 0 , 0
9446.634   0.045       09446.634   0.045       010600.97   0.045       0
#XS Ineff= 2 , 0
       09898.565        10060.67       0
Bank Sta=9446.634,10600.97
Exp/Cntr=0.3,0.1

Type RM Length L Ch R = 1 ,2889.474,147.081900,147.081900,147.081900
XS GIS Cut Line= 6
1271891.94440925622126.1589995471271614.83989081621669.312359571
1271468.11843345621596.9681413321271344.74239987621525.177701935
1271224.13804948621443.1710148011271070.78373235621323.858204842
#Sta/Elev= 30
9418.05436.416599557.11335.708619591.64833.890269626.18235.725469653.04333.88488
9741.70332.917329787.34535.074459798.856 33.56119844.90233.205069880.87834.27309
9940.83232.777769954.92335.051359973.17635.0793310002.3829.9574410012.0431.82944
10020.6935.4826410024.3536.09213   10039 33.006210162.9536.4915310244.82 40.7153
10324.6543.4400210435.7749.1392310448.7850.6538910464.4550.1034510472.6452.41881
 10544.859.3296410560.5660.1023510573.1761.5234110581.5763.5107210598.9264.54291
#Mann= 3 , 0 , 0
9418.054  0.0469       09418.054  0.0469       010598.92  0.0469       0
#XS Ineff= 2 , 0
       09793.383        10030.12       0
Bank Sta=9418.054,10598.92
Exp/Cntr=0.3,0.1

Type RM Length L Ch R = 1 ,2742.392,193.017200,193.017200,193.017200
XS GIS Cut Line= 6
1271935.34718704622106.6277495321271732.00178054621617.764348507
1271665.92132038621539.4244894981271566.06480891 621452.49630478
1271479.72087836  621369.32221971271251.62949979621124.375371963
#Sta/Elev= 30
9381.891 36.33989411.33635.386139517.93635.269849667.17632.46147 9702.7133.64806
9726.92231.091619752.45632.14405 9766.6730.749679803.80530.531139917.00931.65443
9972.82130.512199998.879 27.6471 10011.429.4294510020.9132.39354 10040.931.07882
10058.5733.3124410080.88 30.640310110.77 31.134910191.0936.1007210291.4239.40913
10363.5143.9049110382.2643.7378110401.4645.1968510427.6944.9601110454.2846.49538
10467.65 48.507510547.3350.3426310578.3252.64415 10591.652.2627610600.9253.44091
#Mann= 3 , 0 , 0
9381.891   0.045       09381.891   0.045       010600.92   0.045       0
#XS Ineff= 2 , 0
       09842.944        10064.18       0
Bank Sta=9381.891,10600.92
Exp/Cntr=0.3,0.1

Type RM Length L Ch R = 1 ,2549.374,144.171500,144.171500,144.171500
XS GIS Cut Line= 6
1271993.94093704  622056.71455511271808.48305392621513.539417848
1271795.47799179621439.9951772991271777.68377167621387.320346281
1271703.03373075621218.5117337111271585.15179133620992.585884079
#Sta/Elev= 30
9363.11135.100149415.36633.728469443.10134.696939498.56934.146879517.94332.80267
9567.90533.021719741.24529.786459758.57931.293579841.78227.939539900.71829.43072
9918.05228.184699958.58128.000349975.09629.17111 10002.124.9488410064.1829.34631
 10092.532.41426 10147.631.8268410167.3633.9054610179.0532.4075510243.3934.98468
10268.9737.5607810287.34 37.077710320.3839.4583910351.3139.5059110364.5741.61999
10379.45 41.4008 10386.942.6675810446.43 43.294110472.47 45.017410506.9845.53573
#Mann= 3 , 0 , 0
9363.111   0.045       09363.111   0.045       010506.98   0.045       0
#XS Ineff= 2 , 0
       0 9823.56        10111.18       0
Bank Sta=9363.111,10506.98
Exp/Cntr=0.3,0.1

Type RM Length L Ch R = 1 ,2405.203,215.634600,215.634600,215.634600
XS GIS Cut Line= 2
1272091.94440928622054.6312217711271803.81506899620929.066985667
#Sta/Elev= 30
 9332.5832.396639367.92932.685769422.11531.753169462.75532.577539483.07430.98951
9550.80731.178249720.13828.140199947.04227.10637   10008  23.68510014.7724.06391
10028.3227.3155110038.4828.6963410065.5729.3872210079.1228.3226810099.4428.91742
10126.5331.4165110140.0831.6697710153.6333.3626910184.1134.9217210224.74 34.6167
10231.5235.5498910238.2934.8169910260.25 35.638310282.3233.7749910319.5735.43981
10356.8234.7600410380.5336.8468510392.5536.3181110458.42 36.775410494.4437.77792
#Mann= 3 , 0 , 0
 9332.58  0.0608       0 9332.58  0.0608       010494.44  0.0608       0
#XS Ineff= 2 , 0
       09903.248        10064.53       0
Bank Sta=9332.58,10494.44
Exp/Cntr=0.3,0.1