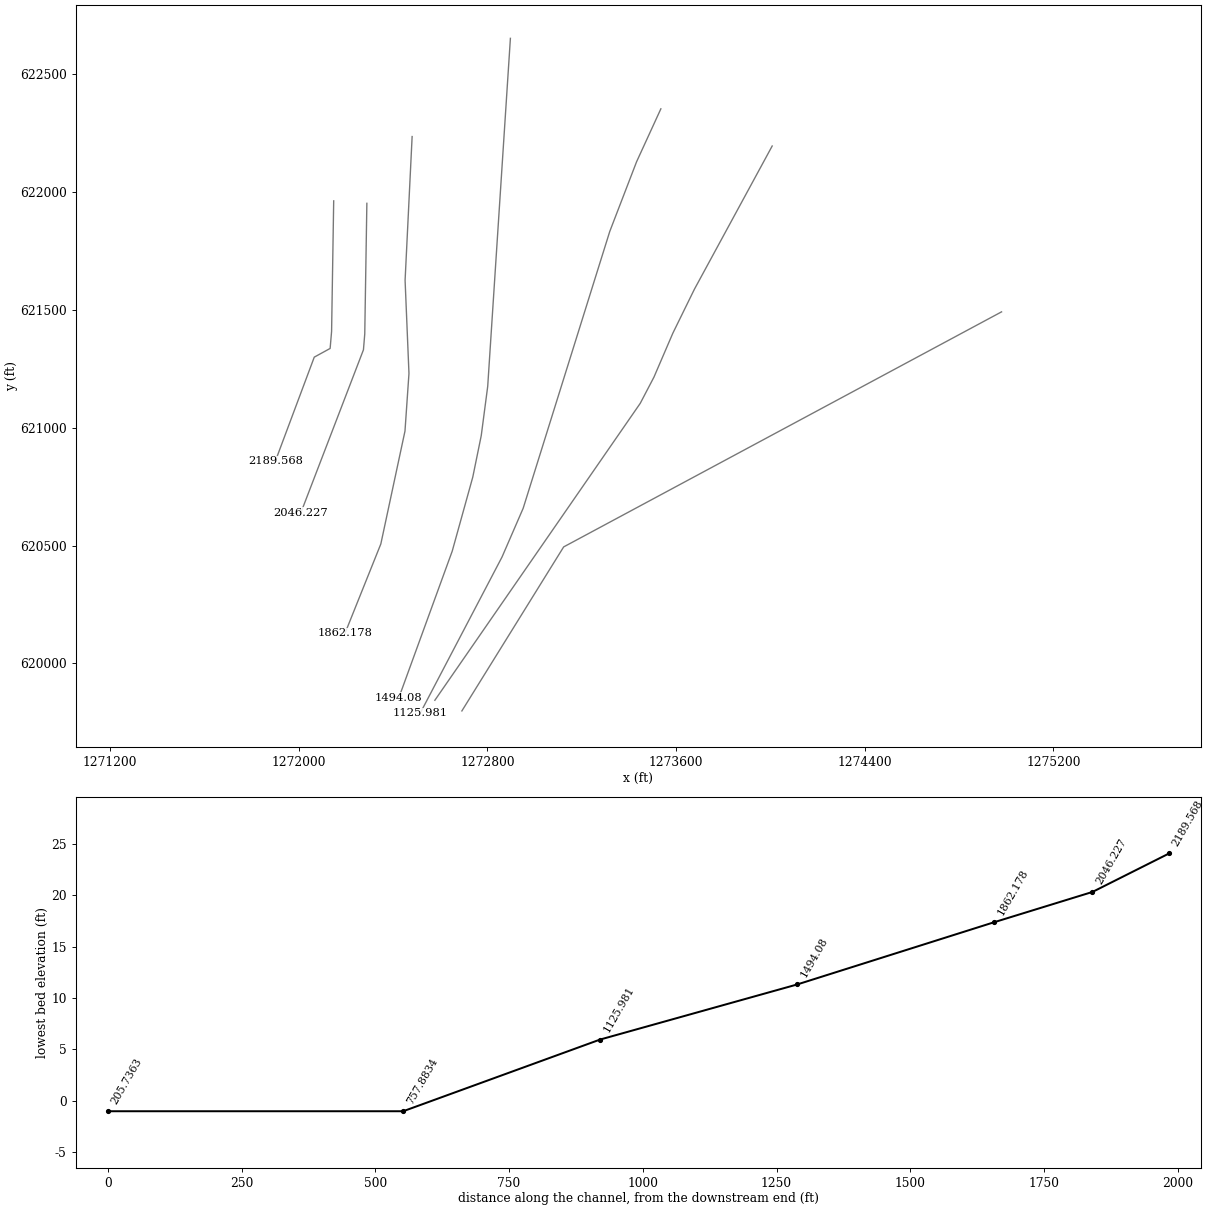
HEC-RAS study 544_ras.prj: 544

--- 544_ras.g01 (geometry) --- (continued)

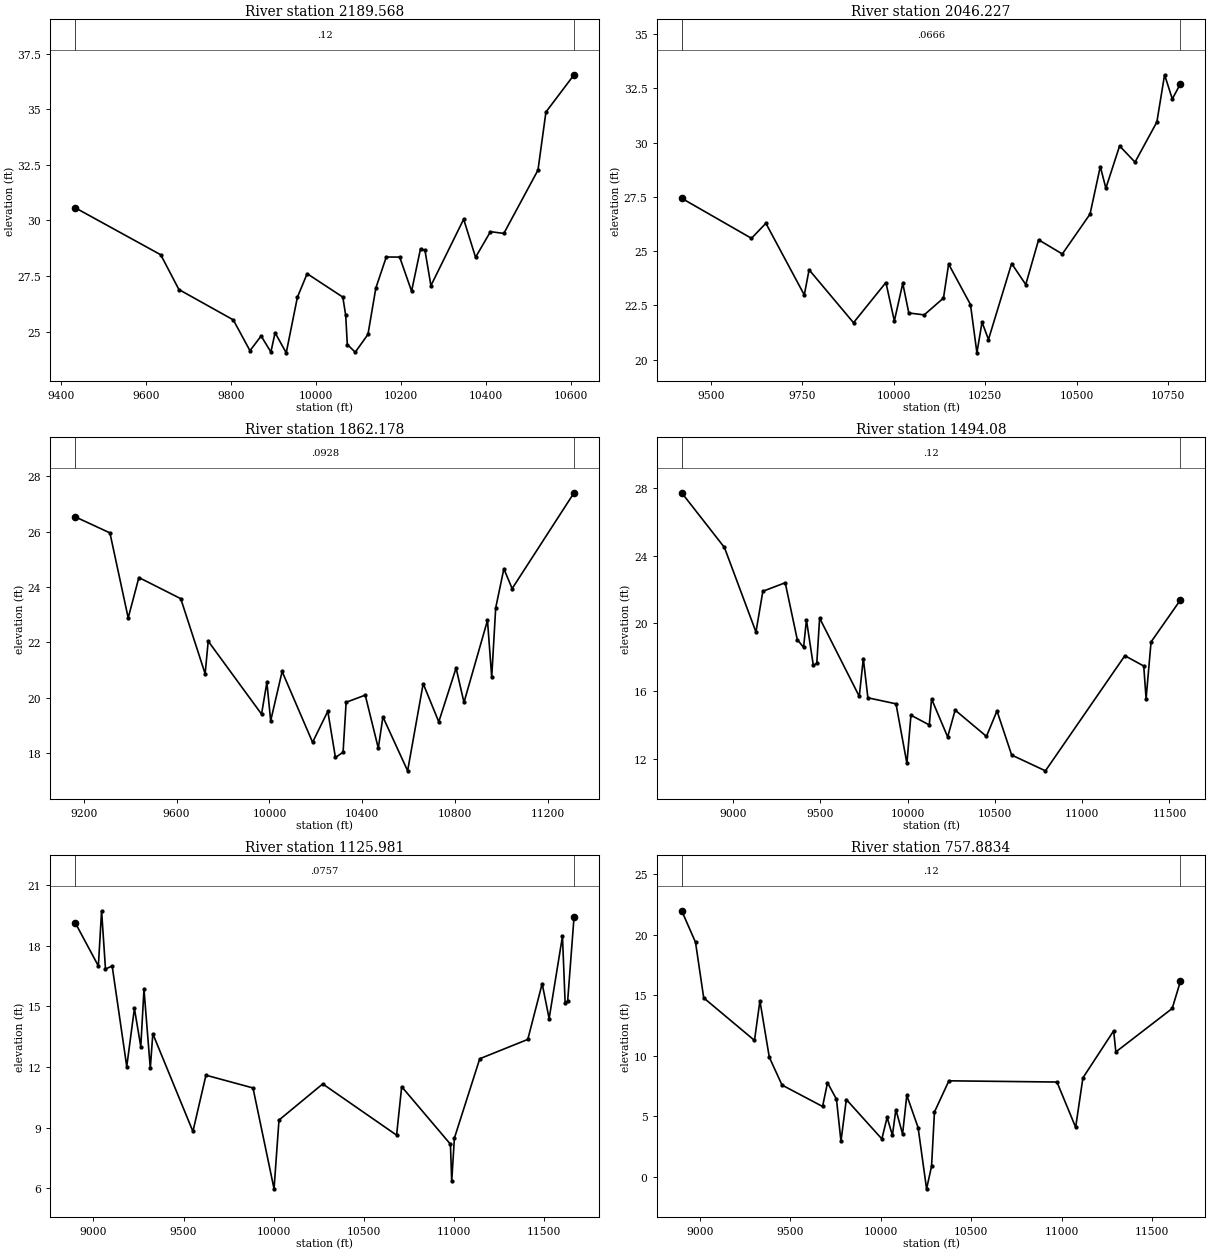
Type RM Length L Ch R = 1 ,2189.568,143.341800,143.341800,143.341800
XS GIS Cut Line= 5
 1272148.3029162621962.3677669171272139.37258074621408.355100587
1272133.19874954621336.2826974391272065.92444399621299.390336335
1271901.03729123620858.320457891
#Sta/Elev= 30
9433.51730.56902 9634.7128.458079677.36726.896999805.33625.534059844.71124.14747
9870.96124.81018 9893.9324.087659903.77424.955259930.02424.051669956.27426.54682
9979.243 27.608810063.2526.5561210070.0225.7326810073.7624.4260610092.47 24.0798
10122.4124.8812410141.0126.9676110165.5328.3586410197.0528.3548710225.0726.82334
10246.0828.7288510256.5928.65906 10270.627.0711110347.6630.0566210375.6828.34651
10410.7129.4973110442.23 29.417910522.5832.2627910541.3234.8738110607.5536.54769
#Mann= 3 , 0 , 0
9433.517    0.12       09433.517    0.12       010607.55    0.12       0
#XS Ineff= 2 , 0
       09947.648        10049.55       0
Bank Sta=9433.517,10607.55
Exp/Cntr=0.3,0.1

Type RM Length L Ch R = 1 ,2046.227,184.049000,184.049000,184.049000
XS GIS Cut Line= 4
 1272288.9279162 621951.951100231272279.99758074621397.938433915
1272274.43385834621330.4836243241272008.61107591620637.964555115
#Sta/Elev= 30
9420.08427.43456 9610.8625.589059650.23526.282789755.23522.97689 9768.3624.13756
9889.76721.697419978.37523.5507210001.4221.7785510024.4623.5135710040.9222.14649
10083.0322.0581210135.7422.83359 10149.824.4001410209.5422.5336910227.1120.30814
10241.17 21.722110258.7420.92242   1032224.4260310360.6523.45757 10395.825.52024
10460.6424.8666810536.3726.7052310564.4828.8991910579.6627.8979910617.1929.84791
10659.3629.1007310719.1130.9510810740.1933.1297410761.2832.0148510783.6432.71862
#Mann= 3 , 0 , 0
9420.084  0.0666       09420.084  0.0666       010783.64  0.0666       0
#XS Ineff= 2 , 0
       09919.966        10098.45       0
Bank Sta=9420.084,10783.64
Exp/Cntr=0.3,0.1

Type RM Length L Ch R = 1 ,1862.178,368.098100,368.098100,368.098100
XS GIS Cut Line= 6
1272480.83329821622235.1867773091272451.01510236621625.322513998
1272467.43524355621230.2853984391272450.55364951620985.735806018
1272348.14929429 620506.861651451272196.11107591620127.547888428
#Sta/Elev= 30
 9163.0926.532539312.419 25.95389391.235 22.88229437.21224.342619617.83323.57852
9723.00920.866039736.16722.044339966.12719.409739989.14220.5534310005.5819.16869
10054.8920.9492410186.2318.39188 10251.919.5132510284.7617.84448 10317.718.03313
10330.8919.83654 10413.320.09584 10469.618.1783210489.4719.3101510596.0417.36144
10663.0920.5098210730.3619.1308110804.9621.0737110838.9919.8323610940.39  22.794
10958.5820.7412710975.75 23.243111011.0124.6578611046.6523.9422211313.7227.40256
#Mann= 3 , 0 , 0
 9163.09  0.0928       0 9163.09  0.0928       011313.72  0.0928       0
#XS Ineff= 2 , 0
       09903.919        10108.94       0
Bank Sta=9163.09,11313.72
Exp/Cntr=0.3,0.1

Type RM Length L Ch R = 1 , 1494.08,368.098100,368.098100,368.098100
XS GIS Cut Line= 6
1272897.49996483622651.8534439951272801.27578399621175.240113854
1272773.88271603620966.5839574781272737.94912207620790.337849379
1272650.87625679620476.4754139931272424.40968701619854.110388428
#Sta/Elev= 30
 8705.0727.701228949.88224.479239130.68519.497519170.13221.897179298.33822.39928
9367.37219.052399403.53218.590529419.96920.206829459.41717.527049479.14117.64528
9495.57720.314519722.72315.704729745.84217.927959772.177 15.61989933.21815.26414
9995.73611.7589410018.8214.5948310123.9714.02011 10137.1 15.552310229.2913.31406
 10272.214.8938510451.6413.3458410511.9314.8474310596.0512.2470710789.5811.31542
11244.8218.1004611353.0517.49149 11366.415.5629611394.9518.9117311563.5221.38801
#Mann= 3 , 0 , 0
 8705.07    0.12       0 8705.07    0.12       011563.52    0.12       0
#XS Ineff= 2 , 0
       09731.938        10131.21       0
Bank Sta=8705.07,11563.52
Exp/Cntr=0.3,0.1

Type RM Length L Ch R = 1 ,1125.981,368.098000,368.098000,368.098000
XS GIS Cut Line= 6
1273535.42818597622352.8261206151273432.33678535622127.916280046
1273318.68232277621832.4180118291272951.68417829620658.372654393
1272861.90968701620451.3326106521272514.68746483619788.138166219
#Sta/Elev= 30
8899.02819.142669027.032 17.00779045.00419.740759066.57116.85526 9103.6817.00458
9184.62512.025579227.12914.900479262.54913.014999280.25915.847989315.35711.93973
9329.33113.648649551.9428.8091269624.28711.596279885.40710.9637310002.265.966632
10029.629.37377910272.46 11.163610682.428.62674510710.6911.0270710981.278.179189
10988.426.33710311003.24 8.4781311143.9612.41067 11410.613.3683911490.5516.13057
11529.11 14.400211603.17 18.479911617.9815.1620711632.0115.2753811667.5719.45686
#Mann= 3 , 0 , 0
8899.028  0.0757       08899.028  0.0757       011667.57  0.0757       0
#XS Ineff= 2 , 0
       09769.901        10139.58       0
Bank Sta=8899.028,11667.57
Exp/Cntr=0.3,0.1

Type RM Length L Ch R = 1 ,757.8834,552.147100,552.147100,552.147100
XS GIS Cut Line= 6
 1274007.4373042622195.1258675611273677.65220219621587.523865491
1273586.39815626621401.4076212641273506.12409291 621214.67176795
 1273447.9977648621103.4406982811272577.18746483619843.693721771
#Sta/Elev= 30
8899.02321.965238975.52319.362589020.83214.76958 9301.6711.259399331.77814.53123
9383.5589.870849 9453.957.5725869678.355 5.802459705.5327.7651579755.0896.405679
9780.0562.9369349809.6936.37824610006.183.12423810035.394.89589310064.613.424488
10083.725.54062510120.94 3.5295810144.21  6.727910206.684.05930910253.54  -0.999
10281.150.86569410297.185.34648710377.097.92224810974.837.822303 11078.24.082872
 11118.48.167213 11288.512.0510611300.49 10.307111612.2913.8955711658.0816.15688
#Mann= 3 , 0 , 0
8899.023    0.12       08899.023    0.12       011658.08    0.12       0
#XS Ineff= 2 , 0
       09875.626        10143.79       0
Bank Sta=8899.023,11658.08
Exp/Cntr=0.3,0.1

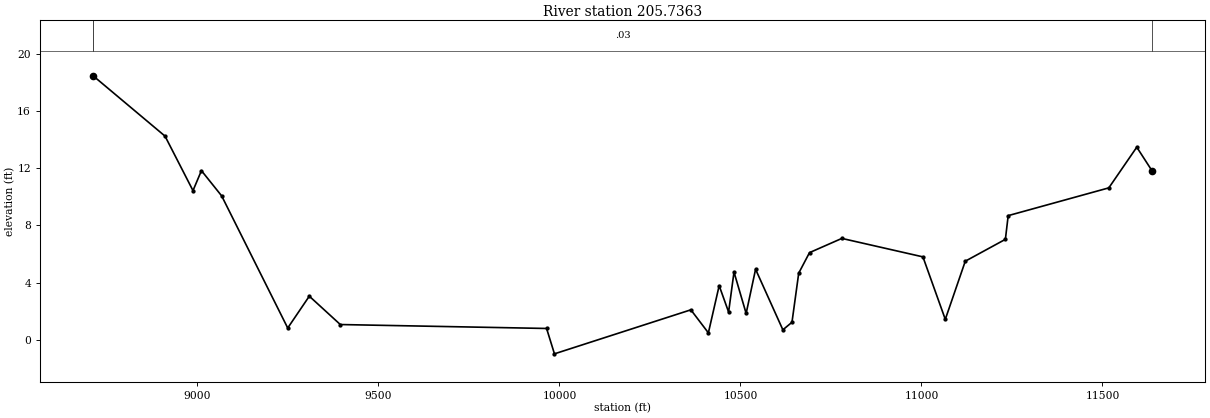
Type RM Length L Ch R = 1 ,205.7363,0.000000,0.000000,0.000000
XS GIS Cut Line= 3
1274979.90013841621491.5344335731273123.25512949620494.262249008
1272691.77079815619798.554832891
#Sta/Elev= 30
8711.92918.491078910.69214.260828987.91710.441359011.244 11.84229067.10710.07189
9249.5910.8114449309.1783.0427589394.8341.0546939964.6310.7790119986.322  -0.999
10363.122.08609710411.530.47153210441.32 3.7805210467.391.93057910482.29 4.73334
10515.811.83255810541.884.92952410617.260.68443110642.431.21472710661.054.656768
10690.846.09490110780.227.09205311004.145.79753711065.911.41788311121.145.494987
11231.917.02672611239.638.687915 11517.610.6345911594.8113.4863911638.1111.78548
#Mann= 3 , 0 , 0
8711.929    0.03       08711.929    0.03       011638.11    0.03       0
#XS Ineff= 2 , 0
       09724.126        10364.78       0
Bank Sta=8711.929,11638.11
Exp/Cntr=0.3,0.1